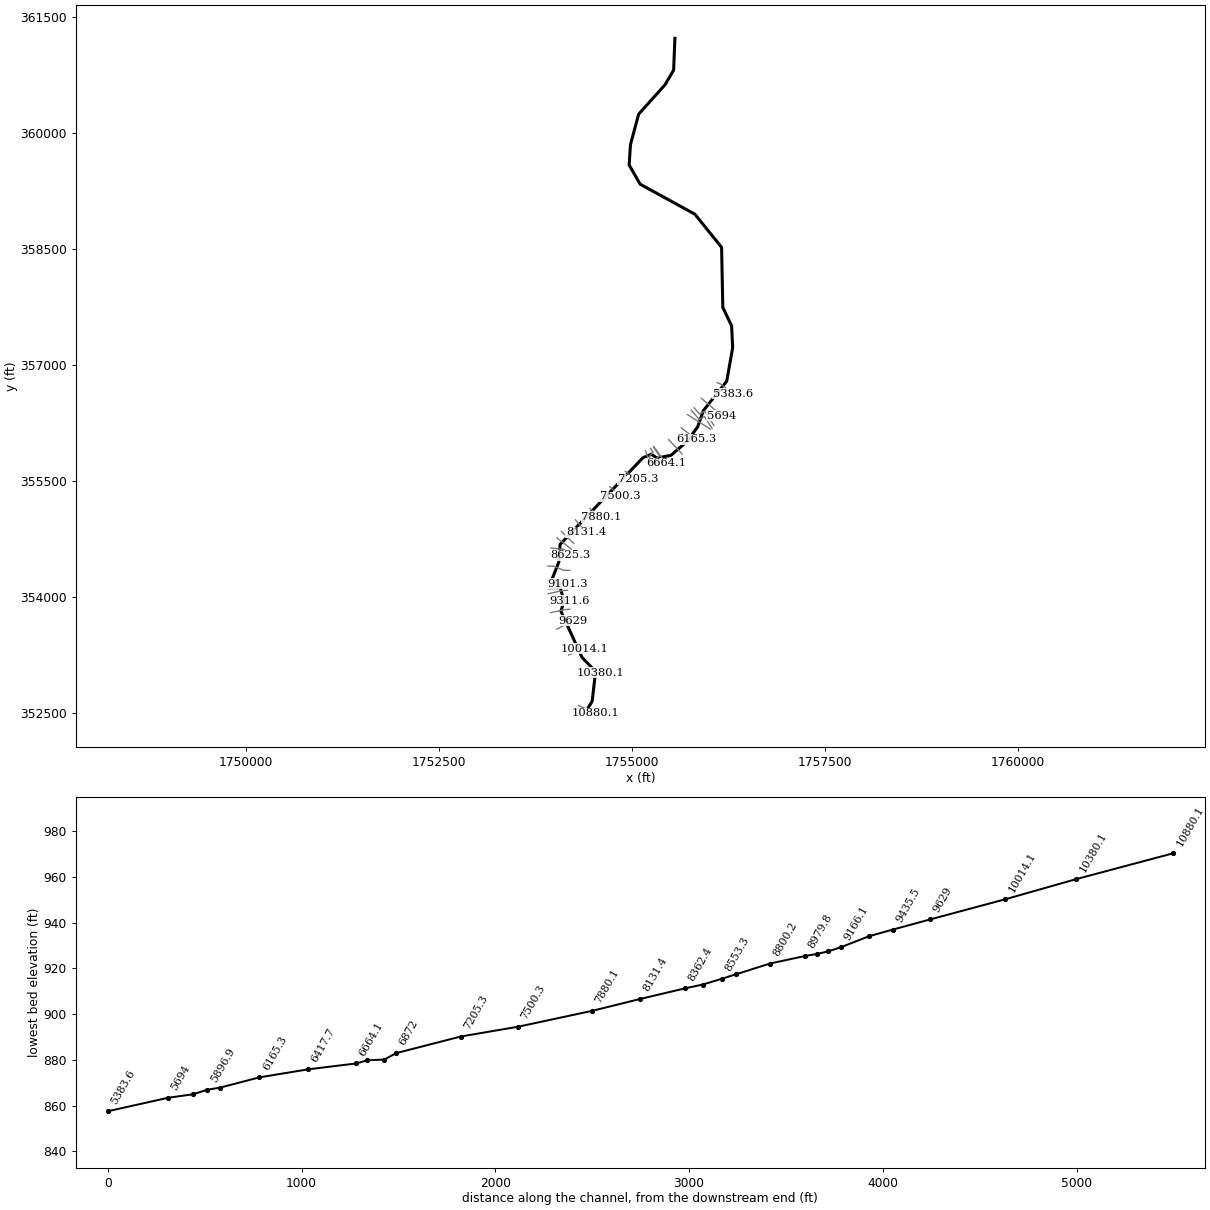
--- BULLCK.prj (project) ---

Proj Title=BULLCK
Current Plan=p01
Default Exp/Contr=0,0
English Units
Geom File=g01
Flow File=f01
Plan File=p01
BEGIN DESCRIPTION:
END DESCRIPTION:
DSS Export Rating Curves= 0
DSS Export Rating Curve Sorted= 0
DSS Export Volume Flow Curves= 0
DXF OffsetX= 0
DXF OffsetY= 0
DXF ScaleX= 0
DXF ScaleY= 0

--- BULLCK.p01 (plan) ---

Plan Title=Floodplain
Program Version=4.00
Geom File=g01
Flow File=f01
K Sum by GR=0
Std Step Tol=0.01
Critical Tol=0.01
Num of Std Step Trials=20
Max Error Tol=0.3
Flow Tol Ratio=0.001
Split Flow NTrial=30
Split Flow Tol=0.02
Split Flow Ratio=0.02
Log Output Level=0
Friction Slope Method=1
Unsteady Friction Slope Method=2
Unsteady Bridges Friction Slope Method=1
Global Log Level=0
CheckData=False
Run HTab=0
Run UNet=0
Run PostProcess=0
UNET Theta=0
UNET Theta Warmup=0
UNET ZTol=0
UNET ZSATol=0
UNET MxIter=0
UNET MaxInSteps=0
UNET DtIC=0
UNET DtMin=0
UNET MaxCRTS=0
UNET WFStab=0
UNET SFStab=0
UNET WFX=0
UNET SFX=0
UNET DSS MLevel=0
UNET DZMax Abort=0
UNET Convert EG Bridges=0
UNET Use Existing IB Tables=0
UNET Froude Limit=0
UNET Froude Power=0
Write IC File=0
Echo Input=False
Echo Output=False
Write Detailed=0

--- BULLCK.f01 (steady flow) ---

Flow Title=NFF Regression Equation
Program Version=4.00
Number of Profiles=1
Profile Names=P100yr
River Rch & RM=BULLCK,Main      ,10880.1
911.8883
River Rch & RM=BULLCK,Main      ,8625.3
978.5204
River Rch & RM=BULLCK,Main      ,8362.4
1149.125
River Rch & RM=BULLCK,Main      ,6872
1238.905
River Rch & RM=BULLCK,Main      ,5383.6
1297.428
River Rch & RM=BULLCK,Main      ,1379.1
1624.971
River Rch & RM=BULLCK,Main      ,1379.1
1400.586
River Rch & RM=BULLCK,Main      ,314.6
1636.264
River Rch & RM=BULLCK,Main      ,96.2
1638.423
Boundary for River Rch & Prof#=BULLCK,Main      ,1
Up Type=0
Dn Type=3
Dn Slope=0.013606

--- BULLCK.g01 (geometry) ---

Geom Title=USGS 10m DEM
Program Version=5.03

River Reach=BULLCK          ,Main
Reach XY= 30
     1754418.611      352540.582     1754486.166      352654.472
     1754530.053      353036.676     1754352.951       353222.02
     1754081.249       353817.68     1754122.048      353946.152
     1754068.228       354138.86     1753970.138      354242.159
     1754054.339      354452.402     1754070.832      354681.569
     1755141.144      355800.232     1755253.124      355847.975
     1755320.832      355798.496     1755505.728      355833.218
     1755714.929      356013.774     1755851.214      356201.708
     1755924.999      356410.909     1756227.082      356791.552
     1756304.339      357224.017      1756290.45      357508.044
     1756176.735      357745.805      1756161.11      358522.888
     1755814.756      358951.708     1755106.422      359339.729
     1754964.929      359587.124     1754981.423      359849.277
     1755087.325      360244.763     1755428.471      360624.624
      1755540.45      360814.729     1755556.566      361225.511

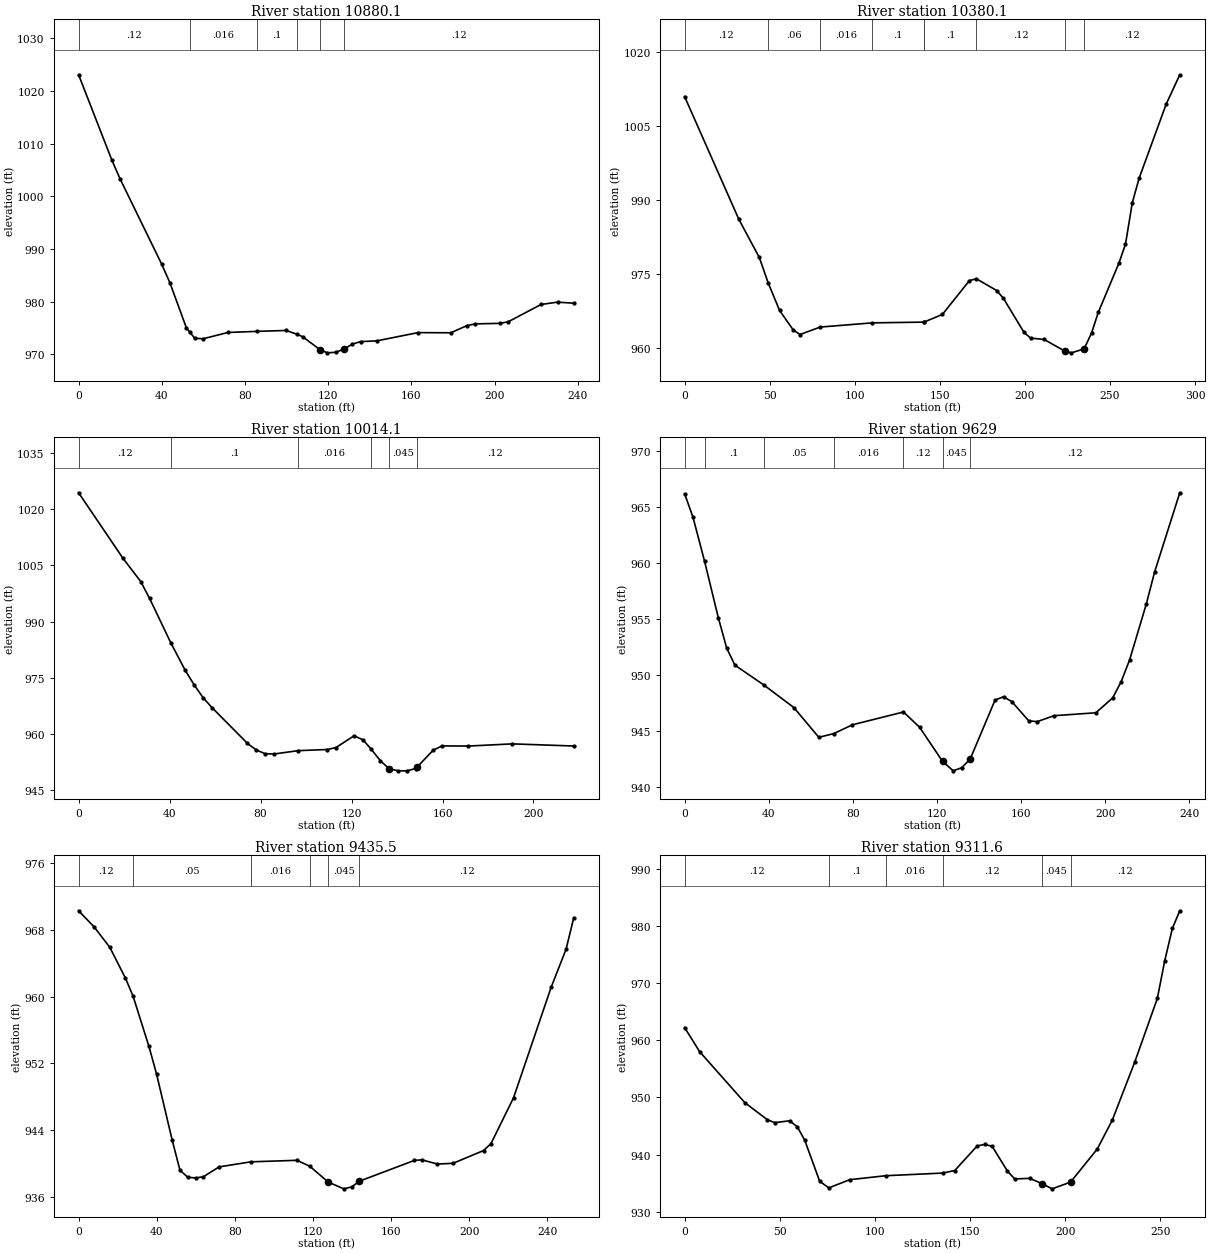
Type RM Length L Ch R = 1 ,10880.1 ,484.5,500,510.9
XS GIS Cut Line= 3
     1754308.923      352598.471     1754422.551      352549.773
     1754523.746      352496.385
#Sta/Elev= 30
       0 1023.09      16 1006.86    19.9 1003.34    39.9  987.14    43.9  983.56
    51.8  975.02   53.47974.1934    55.8  973.04    59.8  972.94    71.8  974.14
    85.6974.3453    99.7  974.52  104.93973.8079   107.7  973.33   116.1  970.85
   119.6  970.27   123.6  970.38   127.6  970.98   131.5  971.92   135.5   972.4
   143.4  972.55   163.1  974.11   178.9  974.08   186.8  975.46   190.7  975.77
   202.5  975.87   206.5  976.17   222.3  979.46   230.2   979.9     238   979.7
#Mann= 6 ,-1 , 0
       0     .12       0   53.47    .016       0    85.6      .1       0
  104.93     .12       0   116.1    .045       0   127.6     .12       0
Bank Sta=116.1,127.6
XS Rating Curve= 0 ,0
Exp/Cntr=0.3,0.1

Type RM Length L Ch R = 1 ,10380.1 ,363.5,366,374.7
XS GIS Cut Line= 3
     1754310.762      352963.258     1754530.047      353022.928
     1754593.804      353022.902
#Sta/Elev= 30
       0 1011.02    31.9  986.07    43.9  978.35   49.04973.2427    55.8   967.6
    63.8  963.65    67.8  962.71   79.65964.2223  110.26965.0767   140.6965.2277
  140.87965.2568   151.5  966.79   167.4  973.67  171.48974.0266   183.4  971.64
   187.4  970.04   199.4  963.17   203.3  961.99   211.3   961.7   223.3  959.37
   227.3  958.99   234.8   959.8   239.2  963.06   243.2  967.29   255.2  977.17
   259.1  981.06   263.1  989.47   267.1  994.43     283 1009.48     291 1015.45
#Mann= 9 ,-1 , 0
       0     .12       0   49.04     .06       0   79.65    .016       0
  110.26      .1       0   140.6     .06       0  140.87      .1       0
  171.48     .12       0   223.3    .045       0   234.8     .12       0
Bank Sta=223.3,234.8
XS Rating Curve= 0 ,0
Exp/Cntr=0.3,0.1

Type RM Length L Ch R = 1 ,10014.1 ,382.9,385.1,387.2
XS GIS Cut Line= 3
     1754179.785      353250.928     1754299.439      353298.789
     1754381.938      353331.789
#Sta/Elev= 30
       0 1024.33    19.5 1006.86    27.3 1000.67    31.2  996.17   40.59984.2521
    46.9  976.96    50.8   973.1    54.7  969.71    58.6  967.07    74.2  957.52
    78.1  955.74      82  954.75    85.9  954.67   96.61 955.564   109.4  955.87
   113.2   956.4   121.1  959.53     125  958.46  128.43956.1205   132.7  952.85
   136.6  950.72   140.5  950.19   144.3  950.18   148.2   950.8   148.7   951.1
   155.9  955.69   159.8  956.83   171.4  956.79   190.7  957.37   217.7   956.8
#Mann= 6 ,-1 , 0
       0     .12       0   40.59      .1       0   96.61    .016       0
  128.43     .12       0   136.6    .045       0   148.7     .12       0
Bank Sta=136.6,148.7
XS Rating Curve= 0 ,0
Exp/Cntr=0.3,0.1

Type RM Length L Ch R = 1 ,9629    ,199.5,193.4,187.3
XS GIS Cut Line= 2
      1754029.29      353586.574     1754238.666       353694.21
#Sta/Elev= 30
       0  966.15       4  964.04    9.47960.1354      16   955.1      20  952.38
    23.9  950.86   37.62949.0947    51.9  947.08    63.8  944.42   70.83944.7485
    79.8  945.54  104.04946.6812   111.7  945.32   122.6  942.28   127.7  941.43
   131.7  941.71   135.7  942.46   147.6  947.75   151.6  948.04   155.6   947.6
   163.6  945.89   167.6  945.82   175.6  946.35   195.5  946.61   203.5  947.94
   207.5  949.37   211.5   951.3   219.5  956.32   223.4  959.15   235.4  966.24
#Mann= 7 ,-1 , 0
       0     .12       0    9.47      .1       0   37.62     .05       0
   70.83    .016       0  104.04     .12       0   122.6    .045       0
   135.7     .12       0
Bank Sta=122.6,135.7
XS Rating Curve= 0 ,0
Exp/Cntr=0.3,0.1

Type RM Length L Ch R = 1 ,9435.5  ,125.3,123.9,122.1
XS GIS Cut Line= 3
     1753946.853      353799.312      1754138.52      353838.896
     1754196.159      353842.715
#Sta/Elev= 30
       0  970.31       8  968.36      16  965.92      24  962.22   27.87960.0818
      36  954.05    39.9  950.74    47.9  942.82    51.9  939.19    55.9  938.36
    59.9  938.28    63.9  938.42    71.9   939.6   88.19940.2087   111.8  940.39
  118.35 939.681   127.8  937.78   135.8  936.97   139.8   937.2   143.8  937.89
   171.8  940.37   175.7  940.45   183.7  939.94   191.7  940.03   207.3  941.56
   211.1  942.38   222.7   947.9   241.9  961.12   249.6  965.72   253.5  969.48
#Mann= 6 ,-1 , 0
       0     .12       0   27.87     .05       0   88.19    .016       0
  118.35     .12       0   127.8    .045       0   143.8     .12       0
Bank Sta=127.8,143.8
XS Rating Curve= 0 ,0
Exp/Cntr=0.3,0.1

Type RM Length L Ch R = 1 ,9311.6  ,144,145.5,146.7
XS GIS Cut Line= 2
     1753928.874      353910.208     1754185.818      353951.874
#Sta/Elev= 30
       0  962.21     7.9     958    31.6  949.11    43.4  946.13    47.3   945.6
    55.2  945.92    59.2  944.89    63.1  942.56      71  935.35    75.8 934.197
    86.8  935.63  105.72936.3227  135.64936.7871     142  937.23   153.8  941.53
   157.8   941.8   161.7  941.45   169.6  937.18   173.5  935.76   181.4  935.86
   187.9  934.94   193.2  934.03   202.9  935.21   216.9  940.98   224.8  946.02
   236.6  956.16   248.5   967.3   252.4  973.91   256.4  979.54   260.3  982.63
#Mann= 6 ,-1 , 0
       0     .12       0    75.8      .1       0  105.72    .016       0
  135.64     .12       0   187.9    .045       0   202.9     .12       0
Bank Sta=187.9,202.9
XS Rating Curve= 0 ,0
Exp/Cntr=0.3,0.1

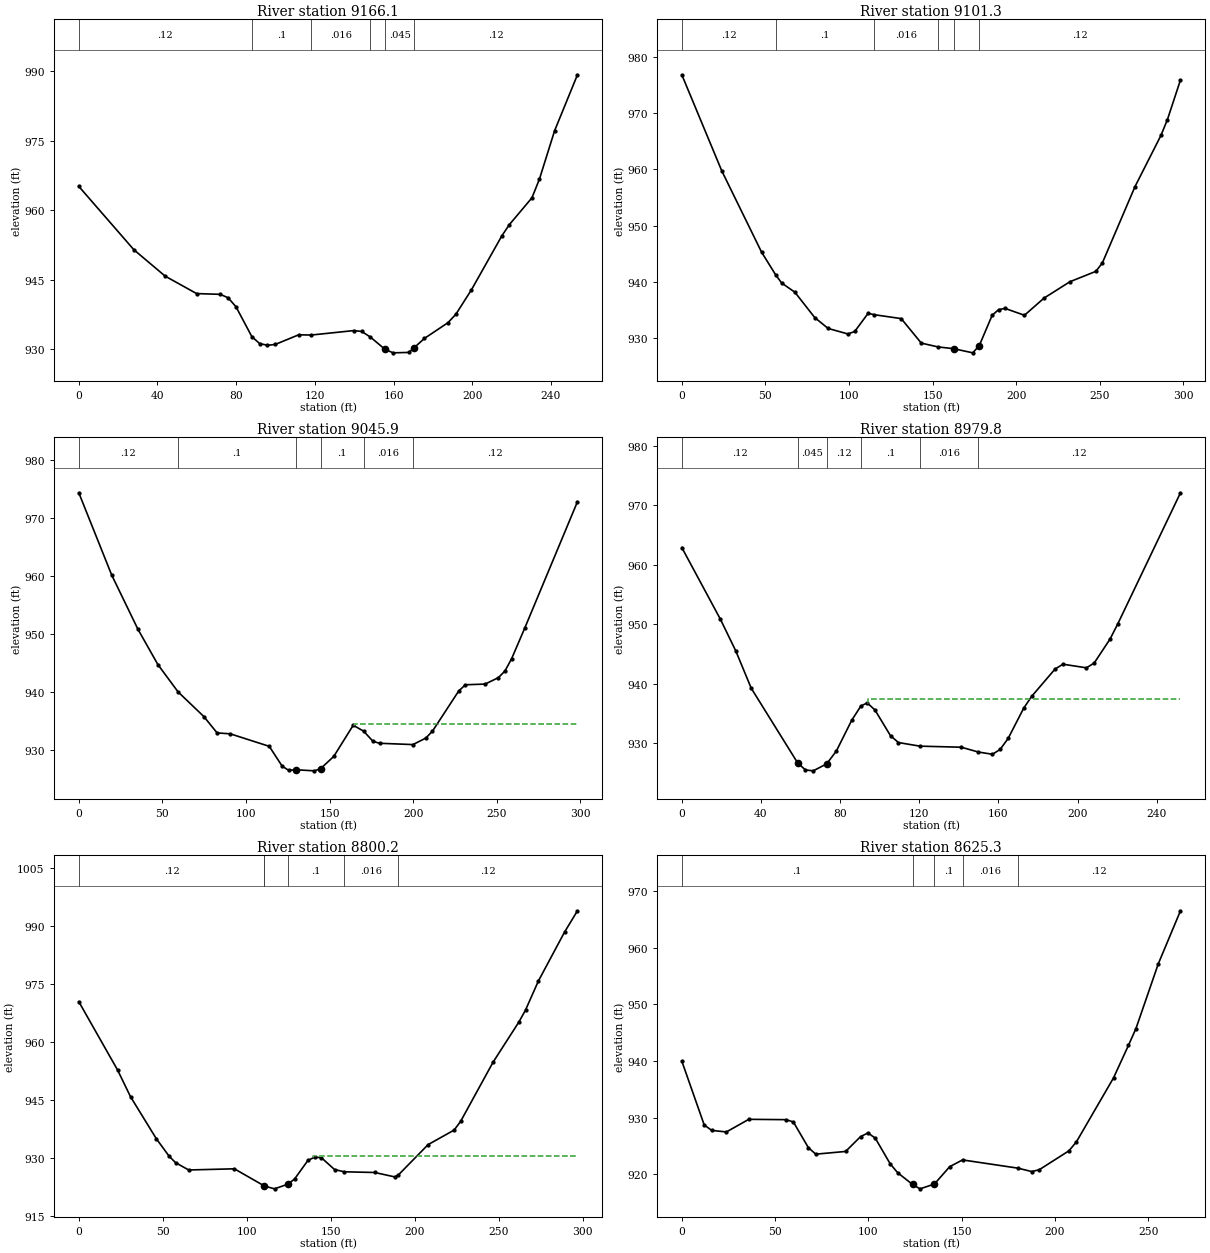
Type RM Length L Ch R = 1 ,9166.1  ,37.4,64.8,94
XS GIS Cut Line= 3
     1753917.556      354044.538     1754109.223      354084.121
     1754166.862      354087.941
#Sta/Elev= 30
       0  965.12      28  951.45    43.9  945.76    59.9  941.99    71.9  941.83
    75.9  941.09    79.9  939.16   87.96932.7172    91.9  931.22    95.9  930.84
    99.8  931.01   111.8   933.1  118.12933.0484   139.8  934.01   143.8  933.83
  148.28 932.596   155.6  929.99   159.8  929.21   167.8   929.3   170.6  930.36
   175.7  932.32   187.7  935.72   191.7  937.54   199.6   942.8     215   954.4
   218.8  956.82   230.4  962.67   234.2  966.72   241.9  977.14   253.5  989.19
#Mann= 6 ,-1 , 0
       0     .12       0   87.96      .1       0  118.12    .016       0
  148.28     .12       0   155.6    .045       0   170.6     .12       0
Bank Sta=155.6,170.6
XS Rating Curve= 0 ,0
Exp/Cntr=0.3,0.1

Type RM Length L Ch R = 1 ,9101.3  ,52.8,55.3,50.4
XS GIS Cut Line= 4
     1753918.037      354106.541     1754061.179      354109.557
     1754071.074      354170.495     1754164.308      354171.439
#Sta/Elev= 30
       0  976.82    23.9  959.75    47.7  945.32   56.14941.2818    59.7  939.84
    67.6  938.21    79.5   933.7    87.5  931.77    99.4  930.79   103.4  931.24
   111.4  934.45  115.22934.2051   131.2  933.52   143.2  929.17   153.1928.4959
   162.5  928.18     174  927.44   177.9  928.74   185.6  934.12   189.5  935.12
   193.3  935.33   204.9  934.11   216.6  937.16   232.1  940.07   247.6  941.91
   251.5  943.42     271  956.96   286.5  966.04   290.4  968.87   298.2   975.9
#Mann= 6 ,-1 , 0
       0     .12       0   56.14      .1       0  115.22    .016       0
   153.1     .12       0   162.5    .045       0   177.9     .12       0
Bank Sta=162.5,177.9
XS Rating Curve= 0 ,0
Exp/Cntr=0.3,0.1

Type RM Length L Ch R = 1 ,9045.9  ,92.5,66.2,44.2
XS GIS Cut Line= 4
     1753914.824      354129.349     1754013.262      354131.432
     1754023.158       354192.37     1754161.179      354193.412
#Sta/Elev= 30
       0  974.34    19.7  960.12    35.4  950.76    47.3  944.68   59.35 939.968
    74.8   935.7    82.7  932.88    90.6  932.72   113.9  930.56   121.6  927.15
   125.5  926.41   129.6  926.52   140.9  926.33   144.6   926.7   152.5  928.83
   164.1   934.2  170.27933.1934     176  931.41   179.9  931.09  199.81930.8631
   207.5  931.98   211.5  933.18   227.2  940.12   231.2  941.19     243  941.31
   250.9  942.42   254.8  943.55   258.8  945.67   266.7  950.99   298.2   972.8
#Mann= 6 ,-1 , 0
       0     .12       0   59.35      .1       0   129.6    .045       0
   144.6      .1       0  170.27    .016       0  199.81     .12       0
#XS Ineff= 2 , 0
                           164.4          934.49
Permanent Ineff=
       F       F
Bank Sta=129.6,144.6
XS Rating Curve= 0 ,0
Exp/Cntr=0.3,0.1

Type RM Length L Ch R = 1 ,8979.8  ,195.6,179.6,164.1
XS GIS Cut Line= 3
       1753916.4      354204.782     1754010.547       354230.57
     1754164.866      354227.295
#Sta/Elev= 30
       0  962.88    19.5  950.84    27.3   945.5    35.1  939.24    58.6  926.68
    62.5  925.53    66.4  925.38    73.2  926.55    78.1  928.71    85.9   933.9
   90.52936.2762    93.7  936.79    97.6   935.6   105.5  931.26   109.5  930.13
  120.31929.5254   141.2  929.35  149.85928.5392     157  928.16   160.9  928.99
   164.9  930.82   172.8  935.92   176.8  937.89   188.6  942.47   192.6  943.29
   204.5  942.68   208.4  943.49   216.4  947.51   220.3  950.05     252  972.08
#Mann= 6 ,-1 , 0
       0     .12       0    58.6    .045       0    73.2     .12       0
   90.52      .1       0  120.31    .016       0  149.85     .12       0
#XS Ineff= 2 , 0
                           94.12          937.43
Permanent Ineff=
       F       F
Bank Sta=58.6,73.2
XS Rating Curve= 0 ,0
Exp/Cntr=0.3,0.1

Type RM Length L Ch R = 1 ,8800.2  ,167.7,174.9,182.1
XS GIS Cut Line= 4
     1753911.179      354400.703     1753991.908      354400.182
      1754112.22      354348.099     1754197.116      354344.974
#Sta/Elev= 30
       0   970.4    23.1  952.75    30.8  945.86    46.1  935.06    53.8  930.49
    57.7  928.82    65.4  926.96    92.6  927.26  110.46922.8288   110.5  922.82
   116.5  922.09   124.4  923.29   128.4  924.61   136.4  929.44   140.3  930.24
   144.3  930.16   152.2  927.08  157.96926.4908   176.1  926.31     188  925.18
  190.14925.6401   207.9   933.5   223.4  937.26   227.3  939.53   246.6   954.8
     262  965.19   265.9  968.25   273.6  975.78   289.1  988.34   296.8  993.86
#Mann= 6 ,-1 , 0
       0     .12       0  110.46      .1       0   110.5    .045       0
   124.4      .1       0  157.96    .016       0  190.14     .12       0
#XS Ineff= 2 , 0
                          139.63          930.54
Permanent Ineff=
       F       F
Bank Sta=110.5,124.4
XS Rating Curve= 0 ,0
Exp/Cntr=0.3,0.1

Type RM Length L Ch R = 1 ,8625.3  ,72.5,72,71.5
XS GIS Cut Line= 2
     1753942.331      354562.333     1754208.824      354541.066
#Sta/Elev= 30
       0  939.98      12   928.7      16  927.73    23.9  927.46    35.9  929.69
    55.9  929.63    59.8  929.22    67.8   924.7    71.8  923.53    87.8  924.01
    95.8  926.63    99.8  927.28   103.7  926.36   111.7  921.82   115.7  920.25
   123.7  918.17   127.7   917.4   135.4  918.25   143.6  921.32  150.47922.5133
   180.1  921.06   187.5  920.46   191.5  920.76   207.5  924.12   211.5   925.7
   231.4  937.01   239.4  942.76   243.4  945.71   255.4  957.18   267.3  966.56
#Mann= 5 ,-1 , 0
       0      .1       0   123.7    .045       0   135.4      .1       0
  150.47    .016       0   180.1     .12       0
Bank Sta=123.7,135.4
XS Rating Curve= 0 ,0
Exp/Cntr=0.3,0.1

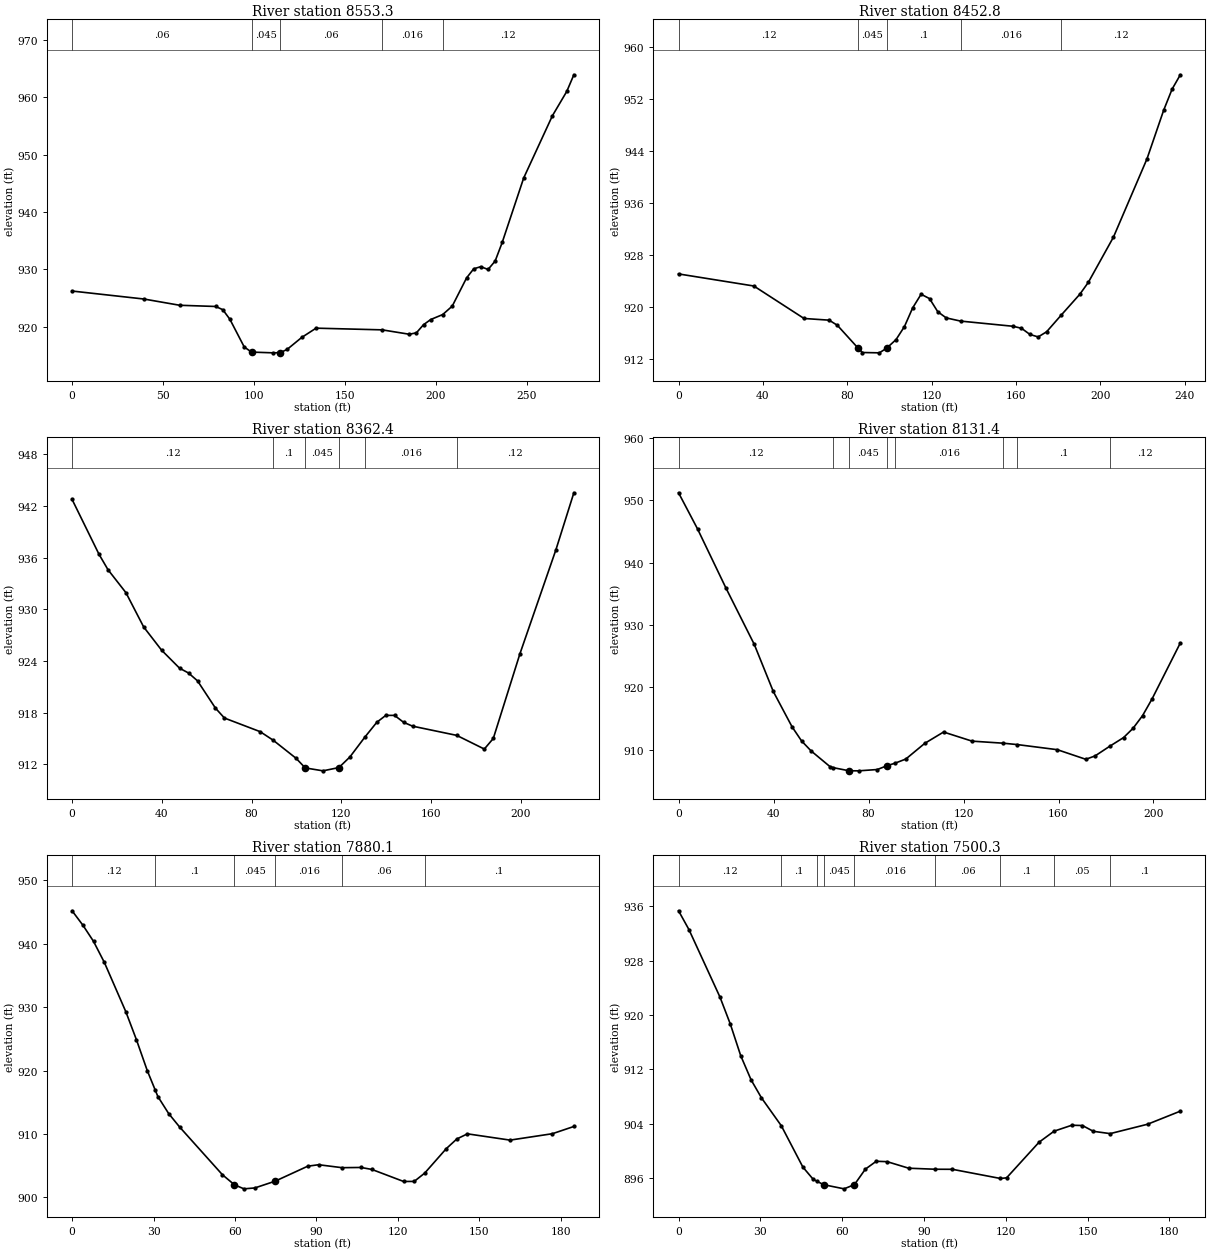
Type RM Length L Ch R = 1 ,8553.3  ,113.8,100.5,87.1
XS GIS Cut Line= 3
     1753953.615      354634.816     1754110.658      354618.412
     1754215.345      354563.724
#Sta/Elev= 30
       0  926.23    39.5  924.84    59.2  923.75      79  923.54    82.9  922.98
    86.8  921.31    94.7  916.48    98.7  915.59   110.5  915.46   114.5  915.49
   118.3  916.06   126.3  918.14   134.2  919.76  170.54919.4663   185.5   918.7
   189.4  918.95   193.3  920.36   197.3  921.27  203.86 922.132   209.1   923.6
     217  928.52   220.9   930.1   224.8  930.48   228.8  929.99   232.7  931.45
   236.6  934.71   248.4  945.93   264.2  956.78   272.1  961.02     276  963.92
#Mann= 5 ,-1 , 0
       0     .06       0    98.7    .045       0   114.5     .06       0
  170.54    .016       0  203.86     .12       0
Bank Sta=98.7,114.5
XS Rating Curve= 0 ,0
Exp/Cntr=0.3,0.1

Type RM Length L Ch R = 1 ,8452.8  ,92.5,90.4,88.3
XS GIS Cut Line= 2
     1754029.873      354766.642     1754216.505      354619.072
#Sta/Elev= 30
       0  925.05    35.7  923.19    59.5  918.19    71.4  917.93    75.3  917.14
   85.25  913.58    87.2  912.95    95.2   912.9    98.6   913.6   103.1  914.93
   107.1  916.94     111  919.82     115  921.92     119  921.25   122.9  919.23
   126.9  918.28  133.69917.7883   158.6  916.99   162.6  916.68   166.6  915.73
   170.5  915.35   174.5  916.14  181.31918.6649   190.3  921.94   194.3  923.76
   206.2  930.72   222.1  942.77     230  950.25     234   953.5   237.9  955.71
#Mann= 5 ,-1 , 0
       0     .12       0   85.25    .045       0    98.6      .1       0
  133.69    .016       0  181.31     .12       0
Bank Sta=85.25,98.6
XS Rating Curve= 0 ,0
Exp/Cntr=0.3,0.1

Type RM Length L Ch R = 1 ,8362.4  ,233.1,231,228.9
XS GIS Cut Line= 2
     1754086.699      354849.141     1754248.158      354694.453
#Sta/Elev= 30
       0  942.78      12  936.41      16  934.62      24  931.95    31.9  927.97
    39.9  925.27    47.9  923.18    51.9  922.62    55.9  921.71    63.9  918.54
    67.9  917.39    83.8  915.81   89.61 914.818    99.8  912.72   103.9   911.6
   111.8  911.26   118.9  911.64   123.8  912.87  130.51915.1891   135.8   916.9
   139.8   917.7   143.7   917.7   147.7   916.9   151.7  916.45  171.41915.3775
   183.7  913.79   187.7  915.02   199.6  924.88   215.6  936.93   223.6  943.55
#Mann= 6 ,-1 , 0
       0     .12       0   89.61      .1       0   103.9    .045       0
   118.9      .1       0  130.51    .016       0  171.41     .12       0
Bank Sta=103.9,118.9
XS Rating Curve= 0 ,0
Exp/Cntr=0.3,0.1

Type RM Length L Ch R = 1 ,8131.4  ,247.6,251.3,257.2
XS GIS Cut Line= 2
     1754269.512      354999.141     1754406.491      354838.203
#Sta/Elev= 30
       0  951.19       8   945.4    19.9  935.97    31.9  926.88    39.9  919.34
    47.8  913.68    51.8  911.42    55.8  909.82    63.8  907.29   65.14907.1292
    71.8  906.63    75.8  906.62    83.7  906.83    87.7  907.43    91.2  907.85
    95.7  908.51   103.7  911.03   111.6  912.84   123.6  911.38  136.77911.0491
  142.71910.8256   159.5  910.01   171.5  908.47   175.4  909.01   181.5 910.543
   187.4  911.95   191.4  913.44   195.4  915.47   199.4  918.15   211.3  927.12
#Mann= 8 ,-1 , 0
       0     .12       0   65.14      .1       0    71.8    .045       0
    87.7      .1       0    91.2    .016       0  136.77     .06       0
  142.71      .1       0   181.5     .12       0
Bank Sta=71.8,87.7
XS Rating Curve= 0 ,0
Exp/Cntr=0.3,0.1

Type RM Length L Ch R = 1 ,7880.1  ,380.6,379.8,376.3
XS GIS Cut Line= 3
     1754457.567      355146.568     1754508.793      355102.974
     1754605.828      355036.703
#Sta/Elev= 30
       0  945.19       4  942.91     7.9  940.37    11.9  937.04    19.8  929.28
    23.7  924.87    27.7  919.99   30.58916.9771    31.6  915.91    35.6  913.21
    39.6  911.11    55.4  903.57    59.8     902    63.3  901.36    67.3   901.5
    74.8  902.57    86.8  904.93    90.8  905.16   99.46904.6934   106.4  904.73
   110.4  904.42   122.1  902.52     126  902.53  129.86903.8364   137.8  907.69
   141.7  909.22   145.6  910.03   161.3  909.04   176.9  910.05   184.8  911.19
#Mann= 6 ,-1 , 0
       0     .12       0   30.58      .1       0    59.8    .045       0
    74.8    .016       0   99.46     .06       0  129.86      .1       0
Bank Sta=59.8,74.8
XS Rating Curve= 0 ,0
Exp/Cntr=0.3,0.1

Type RM Length L Ch R = 1 ,7500.3  ,290.9,295,299
XS GIS Cut Line= 3
     1754714.391      355426.833     1754761.905      355383.153
     1754849.603      355302.097
#Sta/Elev= 30
       0  935.31     3.8  932.56    15.2  922.63      19  918.66    22.8  914.03
    26.6  910.48    30.4  907.84   37.69903.7338    45.6  897.66    49.4  895.86
   50.64895.6047    53.2  895.08    60.7  894.47    64.5  895.09    68.5  897.36
    72.5  898.52    76.5  898.46    84.4   897.5    94.2897.3475   100.4  897.34
  118.06895.9892   120.3  896.09   132.2  901.32  137.72902.9412   144.2  903.81
   148.1  903.77   152.1  902.92  158.28902.5799     172  903.96     184  905.88
#Mann= 9 ,-1 , 0
       0     .12       0   37.69      .1       0   50.64    .016       0
    53.2    .045       0    64.5    .016       0    94.2     .06       0
  118.06      .1       0  137.72     .05       0  158.28      .1       0
Bank Sta=53.2,64.5
XS Rating Curve= 0 ,0
Exp/Cntr=0.3,0.1

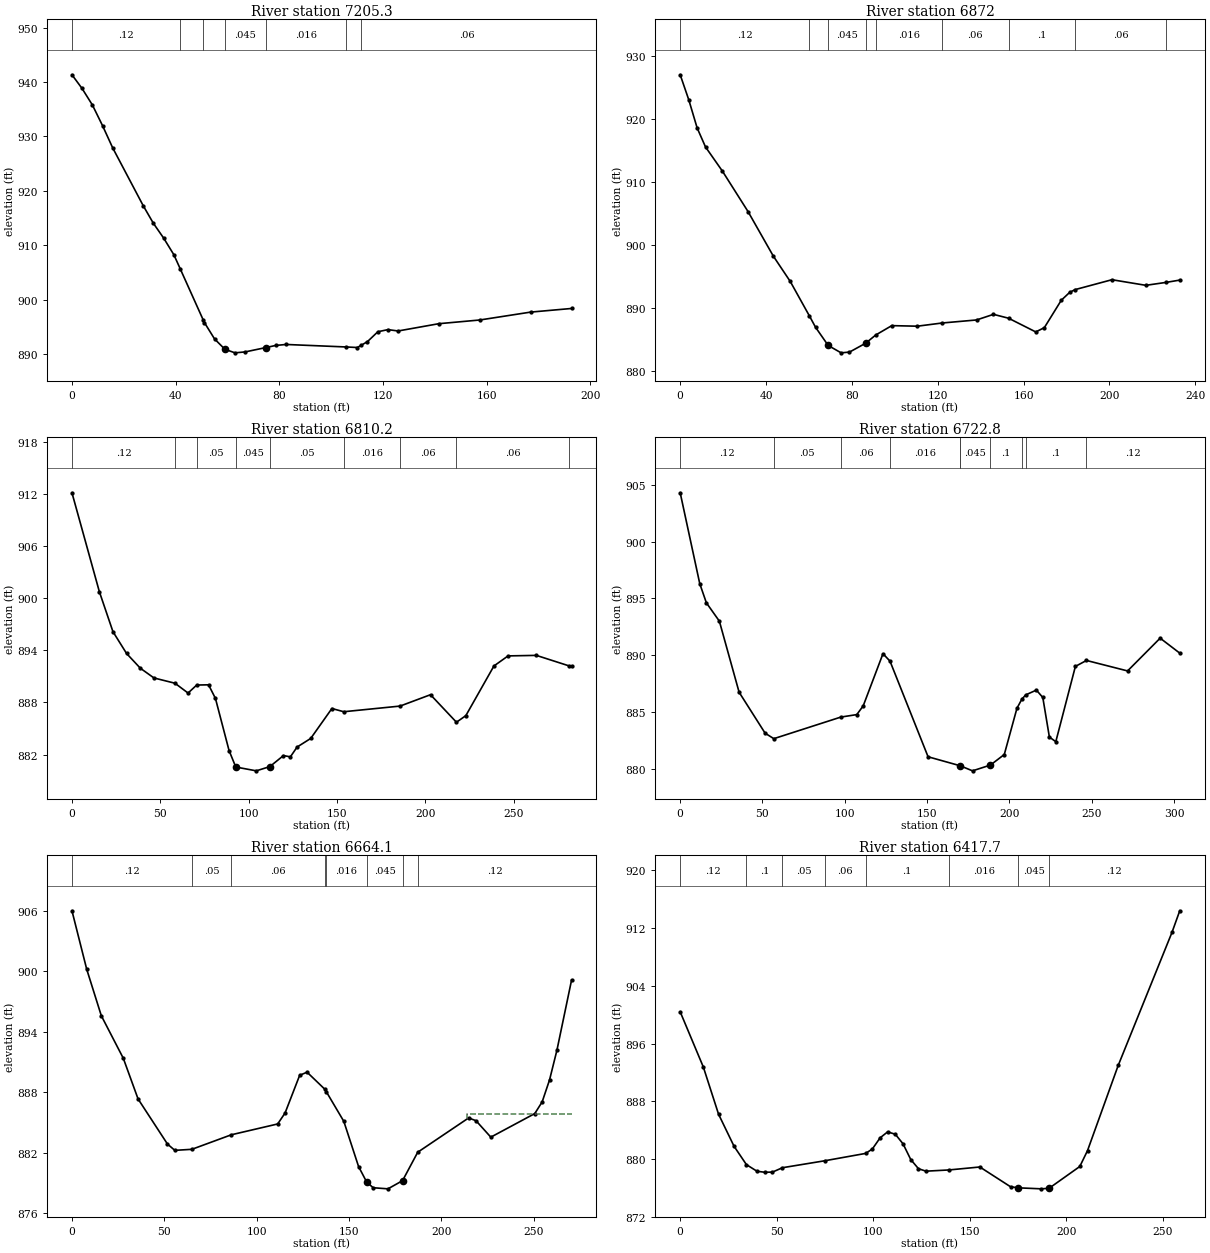
Type RM Length L Ch R = 1 ,7205.3  ,349.3,333.3,317.4
XS GIS Cut Line= 2
     1754913.665      355626.352     1755076.426      355523.271
#Sta/Elev= 30
       0  941.34     3.9  938.82     7.9  935.77    11.8  931.98    15.7  927.91
    27.5  917.25    31.4  914.03    35.4  911.28    39.3  908.25   41.71905.7103
   50.56896.3235    51.1  895.76      55  892.76      59  890.85    62.9   890.2
    66.8  890.37    74.7  891.16    78.6  891.56    82.6  891.74  105.76891.2798
   110.1  891.18  111.63891.6076     114  892.27     118  894.08   121.9  894.47
   125.8  894.22   141.5  895.56   157.3  896.24   176.9  897.69   192.7  898.36
#Mann= 7 ,-1 , 0
       0     .12       0   41.71      .1       0   50.56    .016       0
      59    .045       0    74.7    .016       0  105.76     .08       0
  111.63     .06       0
Bank Sta=59,74.7
XS Rating Curve= 0 ,0
Exp/Cntr=0.3,0.1

Type RM Length L Ch R = 1 ,6872    ,90.2,61.8,27
XS GIS Cut Line= 2
     1755176.729      355893.039     1755246.174      355670.817
#Sta/Elev= 30
       0  927.09       4  923.12     7.9  918.65    11.8  915.63    19.7  911.78
    31.6  905.38    43.4   898.3    51.3  894.27    60.2888.8118    63.1  886.99
   68.97  884.11      75  882.94    78.9  883.06    86.4  884.46   91.14885.7745
    98.6  887.26   110.5  887.17  122.09887.6787   138.1  888.16     146  889.05
  153.03 888.436   165.7  886.26   169.7  886.94   177.6  891.29   181.5  892.54
  183.98 892.974   201.2  894.55     217  893.66   226.4894.1237   232.8  894.49
#Mann= 9 ,-1 , 0
       0     .12       0    60.2      .1       0   68.97    .045       0
    86.4      .1       0   91.14    .016       0  122.09     .06       0
  153.03      .1       0  183.98     .06       0   226.4     .12       0
Bank Sta=68.97,86.4
XS Rating Curve= 0 ,0
Exp/Cntr=0.3,0.1

Type RM Length L Ch R = 1 ,6810.2  ,100,87.4,100.9
XS GIS Cut Line= 4
     1755242.602      355923.794     1755277.777      355868.254
     1755224.882      355823.357     1755280.449      355686.641
#Sta/Elev= 30
       0  912.15    15.5  900.76    23.2  896.15    30.9  893.64    38.7  891.94
    46.4  890.82   58.31890.2108    65.7  889.08    70.6890.0026    77.3  890.03
    81.2  888.46    88.9  882.46    92.7  880.56   104.3  880.12     112  880.61
   119.7  881.88   123.6  881.73   127.4  882.86   135.1  883.85   147.1   887.3
  153.81 886.929  185.69887.5803   202.9  888.89  217.58885.7184   222.9  886.48
   238.8   892.2   246.8  893.36   262.8  893.42  281.34892.2074   282.7  892.17
#Mann= 9 ,-1 , 0
       0     .12       0   58.31      .1       0    70.6     .05       0
    92.7    .045       0     112     .05       0  153.81    .016       0
  185.69     .06       0  217.58     .06       0  281.34     .12       0
Bank Sta=92.7,112
XS Rating Curve= 0 ,0
Exp/Cntr=0.3,0.1

Type RM Length L Ch R = 1 ,6722.8  ,12,58.7,94.2
XS GIS Cut Line= 4
     1755279.439      355942.249     1755355.555      355825.893
     1755302.659      355780.996       1755346.8      355696.763
#Sta/Elev= 30
       0  904.32    11.9   896.3    15.9  894.62    23.8     893    35.8  886.73
    51.6  883.12   56.88882.6372   97.61884.5408   107.3  884.76   111.2  885.53
   123.2  890.13  127.47889.4725   150.6  881.04  169.72880.2632   169.9  880.26
   177.6   879.8   188.5  880.31   196.9  881.24   204.6  885.32  207.53886.1065
  209.88886.4954   216.4  886.92   220.3  886.27   224.3  882.78   228.2  882.37
   240.1  889.01  246.84889.5335   271.8  888.61   291.6   891.5   303.5  890.18
#Mann= 10 ,-1 , 0
       0     .12       0   56.88     .05       0   97.61     .06       0
  127.47    .016       0  169.72      .1       0   169.9    .045       0
   188.5      .1       0  207.53     .06       0  209.88      .1       0
  246.84     .12       0
Bank Sta=169.9,188.5
XS Rating Curve= 0 ,0
Exp/Cntr=0.3,0.1

Type RM Length L Ch R = 1 ,6664.1  ,243.7,246.5,248.8
XS GIS Cut Line= 2
     1755282.359      355947.274     1755440.706      355727.934
#Sta/Elev= 30
       0     906       8  900.19    15.9  895.58    27.8  891.36    35.8  887.32
    51.7  882.85    55.7  882.22   64.91882.3226    86.3 883.766   111.4  884.84
   115.4  885.93   123.3  889.67   127.3  889.98  136.76888.3145  137.77 888.027
   147.2   885.1   155.2  880.61   159.6  879.07   163.1  878.51   171.1   878.4
     179  879.21  187.22882.0329   214.8  885.44   218.8  885.16   226.8  883.53
   250.6  885.87   254.6  887.03   258.6  889.21   262.6  892.16   270.5   899.1
#Mann= 8 ,-1 , 0
       0     .12       0   64.91     .05       0    86.3     .06       0
  136.76      .1       0  137.77    .016       0   159.6    .045       0
     179      .1       0  187.22     .12       0
#XS Ineff= 2 , 0
                          213.93          885.82
Permanent Ineff=
       F       F
Bank Sta=159.6,179
XS Rating Curve= 0 ,0
Exp/Cntr=0.3,0.1

Type RM Length L Ch R = 1 ,6417.7  ,248.8,252.4,256
XS GIS Cut Line= 2
     1755473.822      356037.799     1755651.026      355849.094
#Sta/Elev= 30
       0   900.4      12  892.74    19.9  886.19    27.9  881.76   34.32879.2106
    39.8  878.29    43.8  878.15    47.8  878.17   52.99 878.779   74.83879.7383
   96.13 880.764    99.6  881.38   103.6  882.92   107.5  883.75   111.5  883.42
   115.5  882.09   119.5  879.91   123.5  878.64   127.4   878.3  139.28878.4694
   155.3  878.88   171.2  876.14   175.2  875.99   187.2  875.85   191.2  875.93
   207.1  878.95   211.1  881.15     227  892.96   254.9  911.43   258.9  914.41
#Mann= 8 ,-1 , 0
       0     .12       0   34.32      .1       0   52.99     .05       0
   74.83     .06       0   96.13      .1       0  139.28    .016       0
   175.2    .045       0   191.2     .12       0
Bank Sta=175.2,191.2
XS Rating Curve= 0 ,0
Exp/Cntr=0.3,0.1

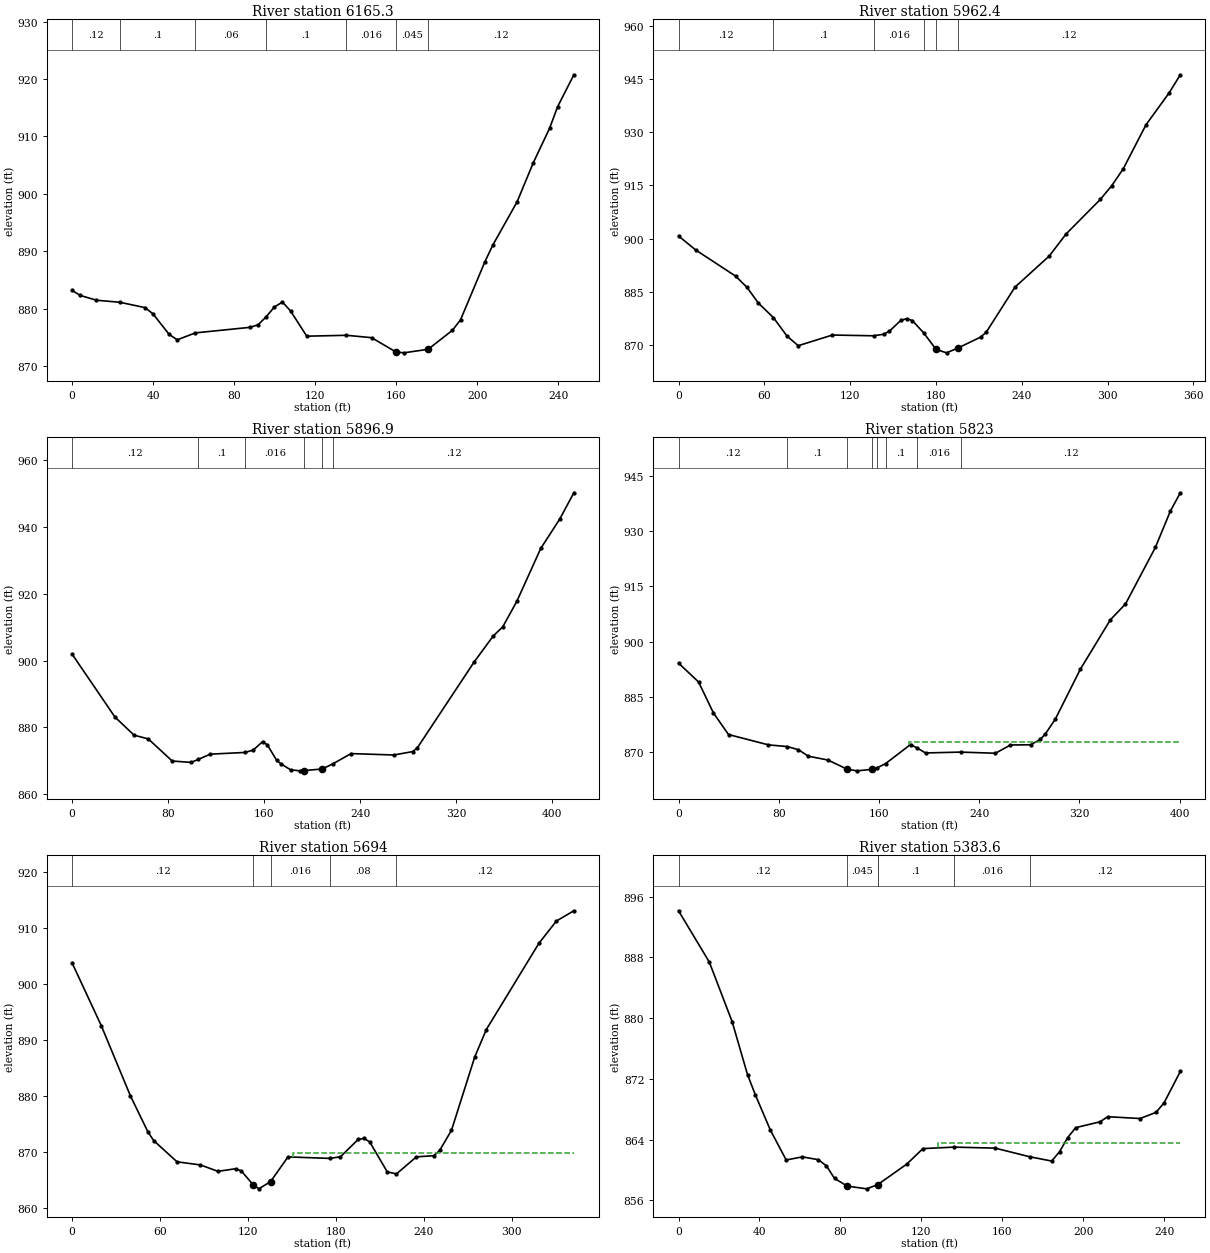
Type RM Length L Ch R = 1 ,6165.3  ,200.7,202.9,204.7
XS GIS Cut Line= 2
     1755639.099      356189.306      1755835.28      356038.265
#Sta/Elev= 30
       0  883.19       4  882.32      12  881.48   23.57881.1254    35.9   880.2
    39.9  879.12    47.9  875.53    51.9  874.59   60.85875.7936    87.8  876.76
    91.8  877.21   95.71878.5687    99.8  880.29   103.8  881.16   107.8  879.62
   115.8  875.22   135.4 875.376   147.8  874.96   159.7  872.49   163.7  872.32
   175.7  872.94   187.7  876.25   191.7  878.08   203.7  888.18   207.7  891.14
   219.6  898.62   227.6  905.43   235.6   911.4   239.6  915.18   247.6  920.73
#Mann= 7 ,-1 , 0
       0     .12       0   23.57      .1       0   60.85     .06       0
   95.71      .1       0   135.4    .016       0   159.7    .045       0
   175.7     .12       0
Bank Sta=159.7,175.7
XS Rating Curve= 0 ,0
Exp/Cntr=0.3,0.1

Type RM Length L Ch R = 1 ,5962.4  ,30.7,65.4,91.5
XS GIS Cut Line= 2
     1755719.936       356359.84     1756015.943      356171.472
#Sta/Elev= 30
       0  900.78      12  896.82    39.9  889.46    47.8  886.32    55.8  881.87
   66.37877.7528    75.8  872.58    83.7  869.84   107.6  872.85  136.38872.6363
   143.5  873.08   147.5  873.94   155.5     877   159.5  877.45   163.5  876.93
  171.39873.4753   180.1  868.81   187.4  867.83   195.1  869.14   211.3  872.27
   215.3  873.72   235.2  886.32   259.2  895.11   271.1  901.38     295  911.09
     303  914.98     311  919.72   326.9  932.11   342.9  941.01   350.9  946.21
#Mann= 6 ,-1 , 0
       0     .12       0   66.37      .1       0  136.38    .016       0
  171.39     .12       0   180.1    .045       0   195.1     .12       0
Bank Sta=180.1,195.1
XS Rating Curve= 0 ,0
Exp/Cntr=0.3,0.1

Type RM Length L Ch R = 1 ,5896.9  ,80,74,73.9
XS GIS Cut Line= 4
     1755768.311       356417.17     1755871.986      356296.884
     1755940.275      356333.515     1756038.218      356180.564
#Sta/Elev= 30
       0  901.93    35.7  883.06    51.6  877.63    63.5  876.49    83.4  869.87
    99.2  869.46  104.96870.3296   115.1  871.93  143.96872.4444   150.9  873.16
   158.8  875.72   162.7  874.69   170.4  870.07   174.3  868.94     182  867.24
   189.8  866.93   193.4  867.03   208.4  867.48  217.38869.0735   232.4   872.1
   267.9  871.68   283.7   872.7   287.6  873.86     335  899.64   350.8  907.37
   358.7   910.1   370.5  917.82   390.3  933.58   406.1  942.37   417.9  950.28
#Mann= 6 ,-1 , 0
       0     .12       0  104.96      .1       0  143.96    .016       0
   193.4    .045       0   208.4    .016       0  217.38     .12       0
Bank Sta=193.4,208.4
XS Rating Curve= 0 ,0
Exp/Cntr=0.3,0.1

Type RM Length L Ch R = 1 ,5823    ,160.7,128.9,99.8
XS GIS Cut Line= 4
      1755807.75      356446.189     1755875.458       356367.63
     1755943.747      356404.262     1756061.656      356219.193
#Sta/Elev= 30
       0  894.14      16  889.03    27.9  880.61    39.9  874.78    71.8  871.98
   86.98871.5103    95.7  870.66   103.7   868.9   119.2  867.88   134.7  865.37
   142.5  864.94   154.1  865.33  158.35 865.726  165.28866.9028   185.2  872.07
  190.13871.1924   197.2  869.79  225.15870.0201     253  869.71     265  871.95
     281     872   288.9  873.45   292.9  874.98   300.9  879.02   320.8   892.5
   344.8  905.91   356.8  910.16   380.7  925.52   392.7   935.4   400.6  940.32
#Mann= 8 ,-1 , 0
       0     .12       0   86.98      .1       0   134.7    .045       0
   154.1      .1       0  158.35    .016       0  165.28      .1       0
  190.13    .016       0  225.15     .12       0
#XS Ineff= 2 , 0
                          184.21          872.67
Permanent Ineff=
       F       F
Bank Sta=134.7,154.1
XS Rating Curve= 0 ,0
Exp/Cntr=0.3,0.1

Type RM Length L Ch R = 1 ,5694    ,310,310.4,311
XS GIS Cut Line= 2
     1755900.491      356569.909     1756160.908      356347.687
#Sta/Elev= 30
       0  903.79    19.9  892.58    39.8  880.02    51.8  873.55    55.7  872.02
    71.6  868.23    87.6  867.67    99.5  866.53   111.5  866.99   115.4  866.62
   123.4  864.16   127.4   863.4   135.4  864.69   147.3  869.11  175.79  868.84
   183.1  869.13   195.1  872.22     199  872.42     203  871.81     215  866.43
  221.29866.0678   234.9  869.12   246.8  869.32   250.8  870.29   258.8  873.85
   274.7  886.98   282.6  891.88   318.5   907.3   330.4  911.27   342.3   913.1
#Mann= 5 ,-1 , 0
       0     .12       0   123.4    .045       0   135.4    .016       0
  175.79     .08       0  221.29     .12       0
#XS Ineff= 2 , 0
                          150.98          869.83
Permanent Ineff=
       F       F
Bank Sta=123.4,135.4
XS Rating Curve= 0 ,0
Exp/Cntr=0.3,0.1

Type RM Length L Ch R = 1 ,5383.6  ,327.4,338.2,347.5
XS GIS Cut Line= 3
     1756104.229      356771.755     1756150.637      356755.295
     1756307.012      356632.692
#Sta/Elev= 30
       0  894.14    15.2  887.39    26.5  879.53    34.1  872.56    37.9  869.94
    45.4  865.25    53.2  861.32    61.2  861.73    69.1  861.36    73.1  860.54
    77.1  858.89    83.4  857.88      93  857.52    98.4  858.07   98.55858.0934
   112.8  860.78   120.8  862.82  136.08863.0146   156.5  862.88  173.61861.7425
   184.4  861.18   188.3   862.4   192.3  864.26   196.3  865.58   208.2  866.34
   212.2  867.02   228.1  866.78     236  867.59     240  868.86     248  872.98
#Mann= 6 ,-1 , 0
       0     .12       0    83.4    .045       0    98.4     .12       0
   98.55      .1       0  136.08    .016       0  173.61     .12       0
#XS Ineff= 2 , 0
                          128.22          863.51
Permanent Ineff=
       F       F
Bank Sta=83.4,98.4
XS Rating Curve= 0 ,0
Exp/Cntr=0.3,0.1