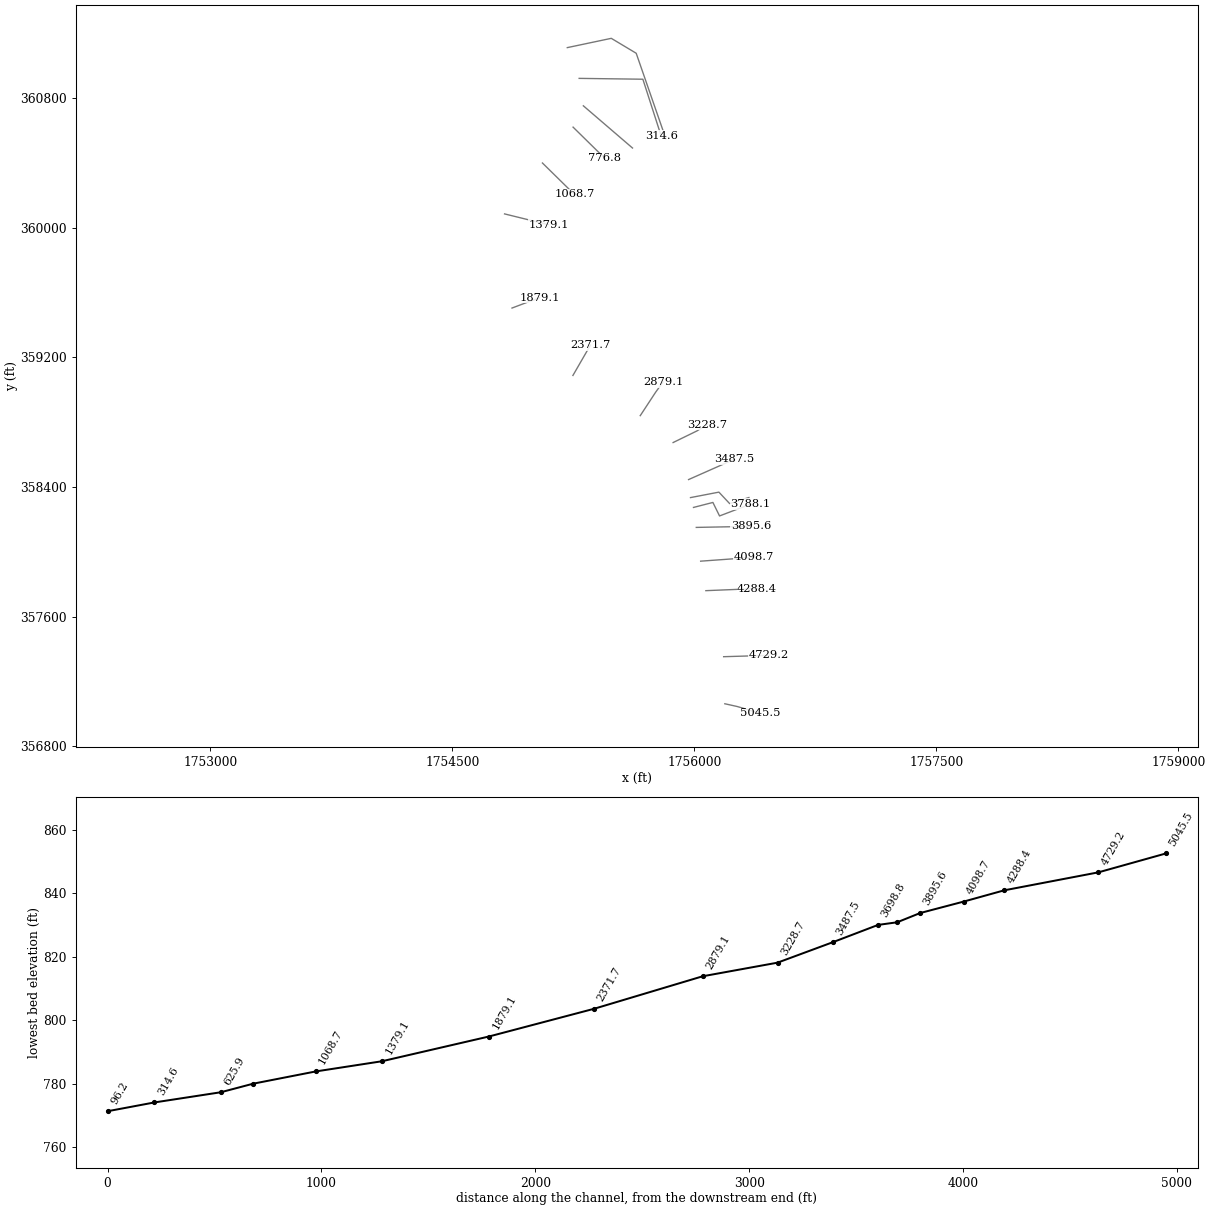
HEC-RAS study BULLCK.prj: BULLCK

--- BULLCK.g01 (geometry) --- (continued)

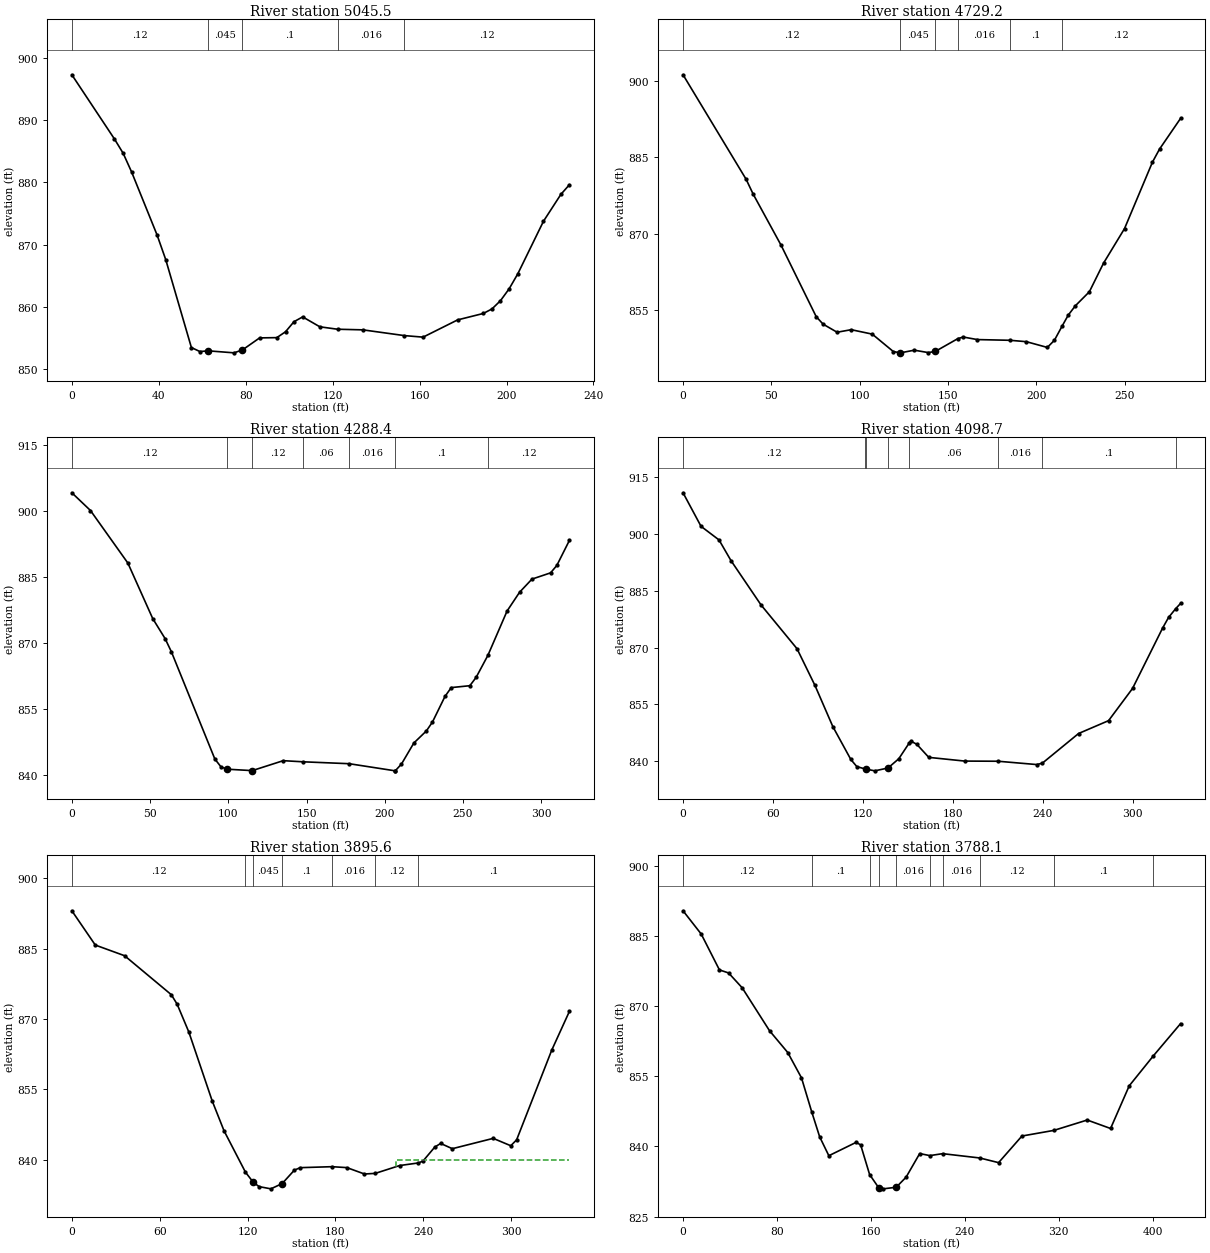
Type RM Length L Ch R = 1 ,5045.5  ,310.5,316.2,322.8
XS GIS Cut Line= 3
      1756188.99      357063.015      1756265.64      357046.053
     1756409.956      357003.685
#Sta/Elev= 30
       0  897.26    19.6  886.95    23.6  884.66    27.5  881.65    39.2  871.55
    43.2  867.58      55  853.47    58.9  852.83    62.8  852.94    74.6  852.62
    78.5  853.09    86.4  855.02    94.3  855.06    98.3     856   102.2  857.62
   106.2  858.39   114.1   856.8  122.23856.4105   133.9  856.31  153.01855.3871
   161.6  855.14   177.5  857.91   189.3  858.94   193.3  859.67   197.2  860.99
   201.2   862.9   205.2  865.32     217  873.75     225  878.06   228.9   879.6
#Mann= 5 ,-1 , 0
       0     .12       0    62.8    .045       0    78.5      .1       0
  122.23    .016       0  153.01     .12       0
Bank Sta=62.8,78.5
XS Rating Curve= 0 ,0
Exp/Cntr=0.3,0.1

Type RM Length L Ch R = 1 ,4729.2  ,440.6,440.8,440.6
XS GIS Cut Line= 2
     1756181.666      357353.387     1756463.137       357361.61
#Sta/Elev= 30
       0  901.19    35.7   880.7    39.7  877.78    55.5  867.76    75.4  853.74
    79.3  852.28    87.2   850.7    95.2   851.2   107.1  850.33     119  846.92
     123  846.66   130.9  847.18   138.8  846.71   142.8  846.94  155.55849.4472
   158.6  849.76   166.6  849.26  185.09849.1204   194.3  848.85   206.2  847.72
   210.2  849.12  214.64851.9519   218.1  854.09   222.1   855.9     230  858.64
     238  864.24   249.9  871.03   265.7  884.06   269.7  886.61   281.6  892.63
#Mann= 6 ,-1 , 0
       0     .12       0     123    .045       0   142.8      .1       0
  155.55    .016       0  185.09      .1       0  214.64     .12       0
Bank Sta=123,142.8
XS Rating Curve= 0 ,0
Exp/Cntr=0.3,0.1

Type RM Length L Ch R = 1 ,4288.4  ,188.9,189.7,190.5
XS GIS Cut Line= 2
     1756071.481      357760.793     1756389.189      357773.813
#Sta/Elev= 30
       0  904.22    11.9  900.19    35.8  888.24    51.7  875.61    59.6  871.06
    63.6  868.08    91.4  843.68    95.4  841.86    99.4  841.36   115.3  841.04
   135.1   843.3  147.66 843.047  177.22842.6136   206.7  840.99  206.78 841.021
   210.7  842.54   218.6  847.32   226.6  850.06   230.5  852.09   238.5  857.91
   242.5  859.92   254.4  860.35   258.4  862.24   265.9 867.227   278.2  877.34
   286.2  881.61   294.1  884.59     306  886.01     310   887.7     318  893.37
#Mann= 7 ,-1 , 0
       0     .12       0    99.4    .045       0   115.3     .12       0
  147.66     .06       0  177.22    .016       0  206.78      .1       0
   265.9     .12       0
Bank Sta=99.4,115.3
XS Rating Curve= 0 ,0
Exp/Cntr=0.3,0.1

Type RM Length L Ch R = 1 ,4098.7  ,204.3,203.1,201.8
XS GIS Cut Line= 2
     1756039.056      357942.779     1756370.002       357966.65
#Sta/Elev= 30
       0  910.96      12  902.09      24  898.49      32  893.01      52  881.31
      76  869.74      88  860.01    99.9  849.14   111.9  840.45   115.9  838.56
  121.21837.9636   121.7  837.92   127.9  837.44   136.7  838.19   143.9  840.64
  150.82844.7897   151.9   845.3   155.9  844.46   163.9     841   187.9  840.02
  210.05839.9786   235.9   839.1  239.66 839.476   263.8  847.31   283.8  850.71
   299.8  859.23   319.8  875.16   323.8  877.99   328.5880.2892   331.8   881.7
#Mann= 8 ,-1 , 0
       0     .12       0  121.21      .1       0   121.7    .045       0
   136.7      .1       0  150.82     .06       0  210.05    .016       0
  239.66      .1       0   328.5     .12       0
Bank Sta=121.7,136.7
XS Rating Curve= 0 ,0
Exp/Cntr=0.3,0.1

Type RM Length L Ch R = 1 ,3895.6  ,137.6,107.5,70.6
XS GIS Cut Line= 2
     1756011.929      358151.112     1756351.556      358157.622
#Sta/Elev= 30
       0  893.06      16  885.76      36  883.49    67.9  875.19    71.9  873.16
    79.9  867.22    95.9   852.5   103.9  846.21  118.52837.4003   123.9  835.22
   127.9  834.31   135.9  833.84   143.6  834.96   151.9  837.81   155.9  838.35
   177.6 838.558   187.8  838.36   199.8     837  207.14837.1301   223.8   838.8
  236.68839.3566   239.8  839.77   247.8  842.73   251.8  843.51   259.8  842.39
   287.7  844.59   299.7  843.02   303.7  844.28   327.7   863.4   339.7  871.61
#Mann= 7 ,-1 , 0
       0     .12       0  118.52      .1       0   123.9    .045       0
   143.6      .1       0   177.6    .016       0  207.14     .12       0
  236.68      .1       0
#XS Ineff= 2 , 0
                          221.05          840.05
Permanent Ineff=
       F       F
Bank Sta=123.9,143.6
XS Rating Curve= 0 ,0
Exp/Cntr=0.3,0.1

Type RM Length L Ch R = 1 ,3788.1  ,94.3,89.3,106.7
XS GIS Cut Line= 4
     1755994.729      358274.372     1756115.041      358305.101
     1756156.187      358221.768     1756349.416      358295.206
#Sta/Elev= 30
       0  890.37    15.5  885.39      31  877.73    38.8  877.08    50.4   873.9
    73.7  864.72    89.2  860.07   100.9  854.66  109.57847.4241   116.4  842.04
   124.2  838.01   147.4  840.86   151.3  840.33  158.93833.9891   166.6  831.19
   170.6  830.93   181.6  831.27     190  833.42   201.6  838.47  210.23838.0338
  221.15838.4499  252.75837.5284   268.8  836.53   288.7  842.22  315.94843.4276
   344.3  845.64   364.2  843.83   380.1  852.96  400.75859.3912   423.8  866.24
#Mann= 10 ,-1 , 0
       0     .12       0  109.57      .1       0  158.93    .016       0
   166.6    .045       0   181.6    .016       0  210.23      .1       0
  221.15    .016       0  252.75     .12       0  315.94      .1       0
  400.75     .12       0
Bank Sta=166.6,181.6
XS Rating Curve= 0 ,0
Exp/Cntr=0.3,0.1

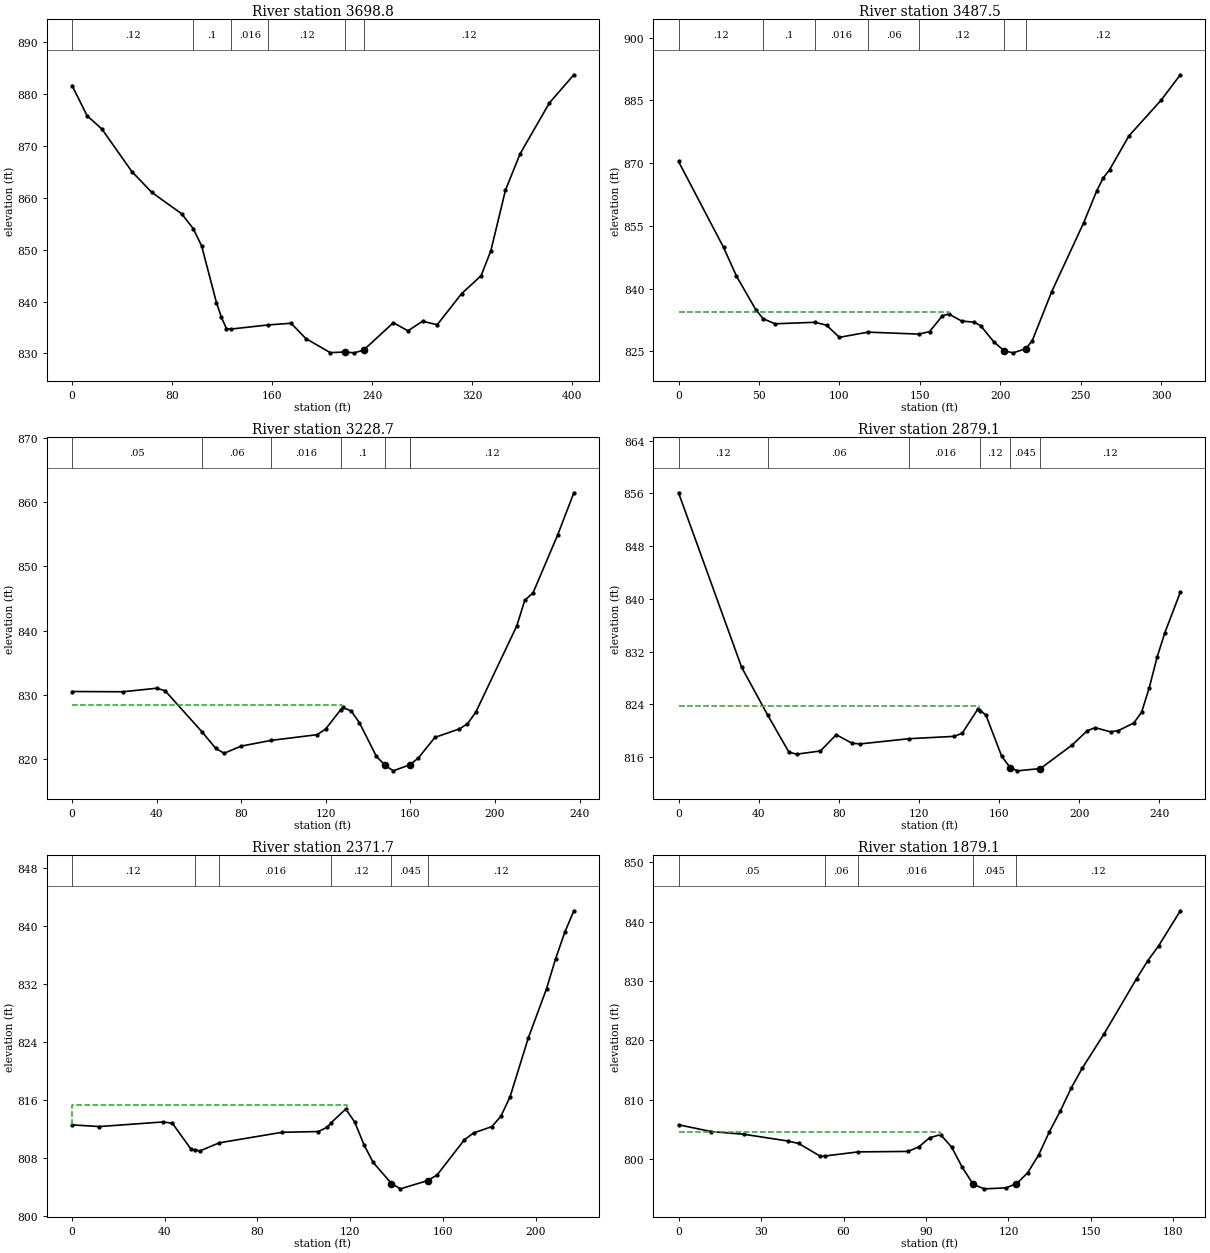
Type RM Length L Ch R = 1 ,3698.8  ,157.3,211.3,251.3
XS GIS Cut Line= 4
     1755976.188      358335.073     1756152.229      358368.754
     1756218.896      358297.921     1756337.993      358335.421
#Sta/Elev= 30
       0  881.69      12  875.86    23.9  873.28    47.8  865.09    63.7  861.08
    87.6  856.94    96.9854.0867   103.6  850.77   115.5  839.79   119.5  836.92
   123.5  834.78  126.97834.6846  157.04835.4896   175.2  835.81     187  832.86
   206.5  830.14   218.3  830.26   225.9   830.1   233.3  830.65     257  835.91
   268.7  834.35   280.4   836.2   292.1  835.52   311.6  841.53   327.2  844.98
     335   849.8   346.7  861.51   358.4  868.52   381.9  878.35   401.4  883.76
#Mann= 6 ,-1 , 0
       0     .12       0    96.9      .1       0  126.97    .016       0
  157.04     .12       0   218.3    .045       0   233.3     .12       0
Bank Sta=218.3,233.3
XS Rating Curve= 0 ,0
Exp/Cntr=0.3,0.1

Type RM Length L Ch R = 1 ,3487.5  ,258.1,258.8,261.1
XS GIS Cut Line= 2
     1755964.186      358446.251     1756249.559      358572.119
#Sta/Elev= 30
       0  870.38      28  849.84      36  843.01      48  834.98   52.58832.8107
      60   831.6   84.86831.9613      92  831.26     100  828.36  117.75829.6063
  149.42829.1351     156  829.72     164  833.51     168  833.94   175.9  832.27
   183.9  831.97   187.9   831.1   195.9  827.32   202.4  825.14   207.9  824.66
   215.9  825.64   219.9   827.6   231.9  839.23   251.9   855.8   259.9  863.33
   263.9  866.43   267.9  868.39   279.9  876.47   299.9  885.01   311.9   891.1
#Mann= 7 ,-1 , 0
       0     .12       0   52.58      .1       0   84.86    .016       0
  117.75     .06       0  149.42     .12       0   202.4    .045       0
   215.9     .12       0
#XS Ineff= 2 , 0
          168.32  834.46
Permanent Ineff=
       F       F
Bank Sta=202.4,215.9
XS Rating Curve= 0 ,0
Exp/Cntr=0.3,0.1

Type RM Length L Ch R = 1 ,3228.7  ,337.3,349.6,359.1
XS GIS Cut Line= 3
     1755868.428      358674.697     1756015.817      358746.272
     1756078.055      358785.343
#Sta/Elev= 30
       0  830.54      24   830.5      40  831.05      44  830.66   61.44 824.274
    67.9  821.72    71.9  820.94    79.9  822.05   94.27822.9489   115.9  823.83
   119.9   824.7  127.11 827.744   127.9  828.06   131.9  827.54   135.9  825.69
   143.9  820.46   148.1  819.06   151.9  818.21   159.8  819.16  159.94819.1969
   163.8  820.22   171.6  823.41   183.2  824.73     187  825.53   190.9  827.31
   210.3  840.73   214.1  844.73     218  845.88   229.6  854.84   237.3  861.43
#Mann= 7 ,-1 , 0
       0     .05       0   61.44     .06       0   94.27    .016       0
  127.11      .1       0   148.1    .045       0   159.8      .1       0
  159.94     .12       0
#XS Ineff= 2 , 0
          127.45  828.45
Permanent Ineff=
       F       F
Bank Sta=148.1,159.8
XS Rating Curve= 0 ,0
Exp/Cntr=0.3,0.1

Type RM Length L Ch R = 1 ,2879.1  ,506,507.4,509.8
XS GIS Cut Line= 3
     1755664.726      358840.647     1755760.016       358985.12
     1755805.348      359047.756
#Sta/Elev= 30
       0  856.08    31.5  829.62   44.44822.4066    55.1  816.75      59  816.46
    70.8  816.94    78.7  819.41    86.5  818.12    90.5  818.01   115.2818.8051
   137.7  819.16   141.6  819.65   149.5  823.35  150.59823.0761   153.4  822.37
   161.3  816.11   165.6   814.4   169.1  813.93   180.6  814.28   196.3  817.82
     204  820.02   207.9  820.47   215.6  819.84   219.5  820.03   227.2  821.19
   231.1  822.83   234.9  826.54   238.8  831.15   242.7  834.88   250.4  841.01
#Mann= 6 ,-1 , 0
       0     .12       0   44.44     .06       0   115.2    .016       0
  150.59     .12       0   165.6    .045       0   180.6     .12       0
#XS Ineff= 2 , 0
          149.85  823.77
Permanent Ineff=
       F       F
Bank Sta=165.6,180.6
XS Rating Curve= 0 ,0
Exp/Cntr=0.3,0.1

Type RM Length L Ch R = 1 ,2371.7  ,508,492.6,476.6
XS GIS Cut Line= 2
     1755247.364      359088.662     1755355.994      359275.967
#Sta/Elev= 30
       0  812.52    11.8  812.29    39.4  812.93    43.3  812.74    51.2  809.22
   52.93809.0869    55.1  808.92   63.49810.0439    90.6   811.5   106.3   811.6
   110.2  812.22  111.81812.8237   118.1  814.71     122  812.88     126  809.74
   129.9  807.35   137.8  804.43   141.7   803.7   153.5  804.85   157.5  805.62
   169.3  810.48   173.2   811.4   181.1  812.28     185  813.69     189  816.42
   196.8  824.47   204.7  831.29   208.6  835.41   212.6   839.1   216.5  842.05
#Mann= 6 ,-1 , 0
       0     .12       0   52.93      .1       0   63.49    .016       0
  111.81     .12       0   137.8    .045       0   153.5     .12       0
#XS Ineff= 2 , 0
          118.68   815.2
Permanent Ineff=
       F       F
Bank Sta=137.8,153.5
XS Rating Curve= 0 ,0
Exp/Cntr=0.3,0.1

Type RM Length L Ch R = 1 ,1879.1  ,513.5,500,487
XS GIS Cut Line= 3
     1754869.772      359504.564      1754977.53      359545.121
     1755040.999      359567.601
#Sta/Elev= 30
       0  805.75    11.9  804.61    23.8  804.15    39.7  803.02    43.7   802.6
    51.6  800.43   53.14800.4839   65.29801.1792    83.4  801.26    87.4  802.03
    91.3  803.56    95.3  804.09    99.3  802.01   103.2  798.57   107.2  795.69
   111.2  794.95   119.1  795.11   122.6  795.78   123.1  795.87     127  797.67
     131  800.69   134.9  804.59   138.9  808.13   142.9  812.02   146.8  815.27
   154.8  821.11   166.6   830.4   170.6  833.38   174.6  835.92   182.5  841.84
#Mann= 5 ,-1 , 0
       0     .05       0   53.14     .06       0   65.29    .016       0
   107.2    .045       0   122.6     .12       0
#XS Ineff= 2 , 0
           95.15  804.59
Permanent Ineff=
       F       F
Bank Sta=107.2,122.6
XS Rating Curve= 0 ,0
Exp/Cntr=0.3,0.1

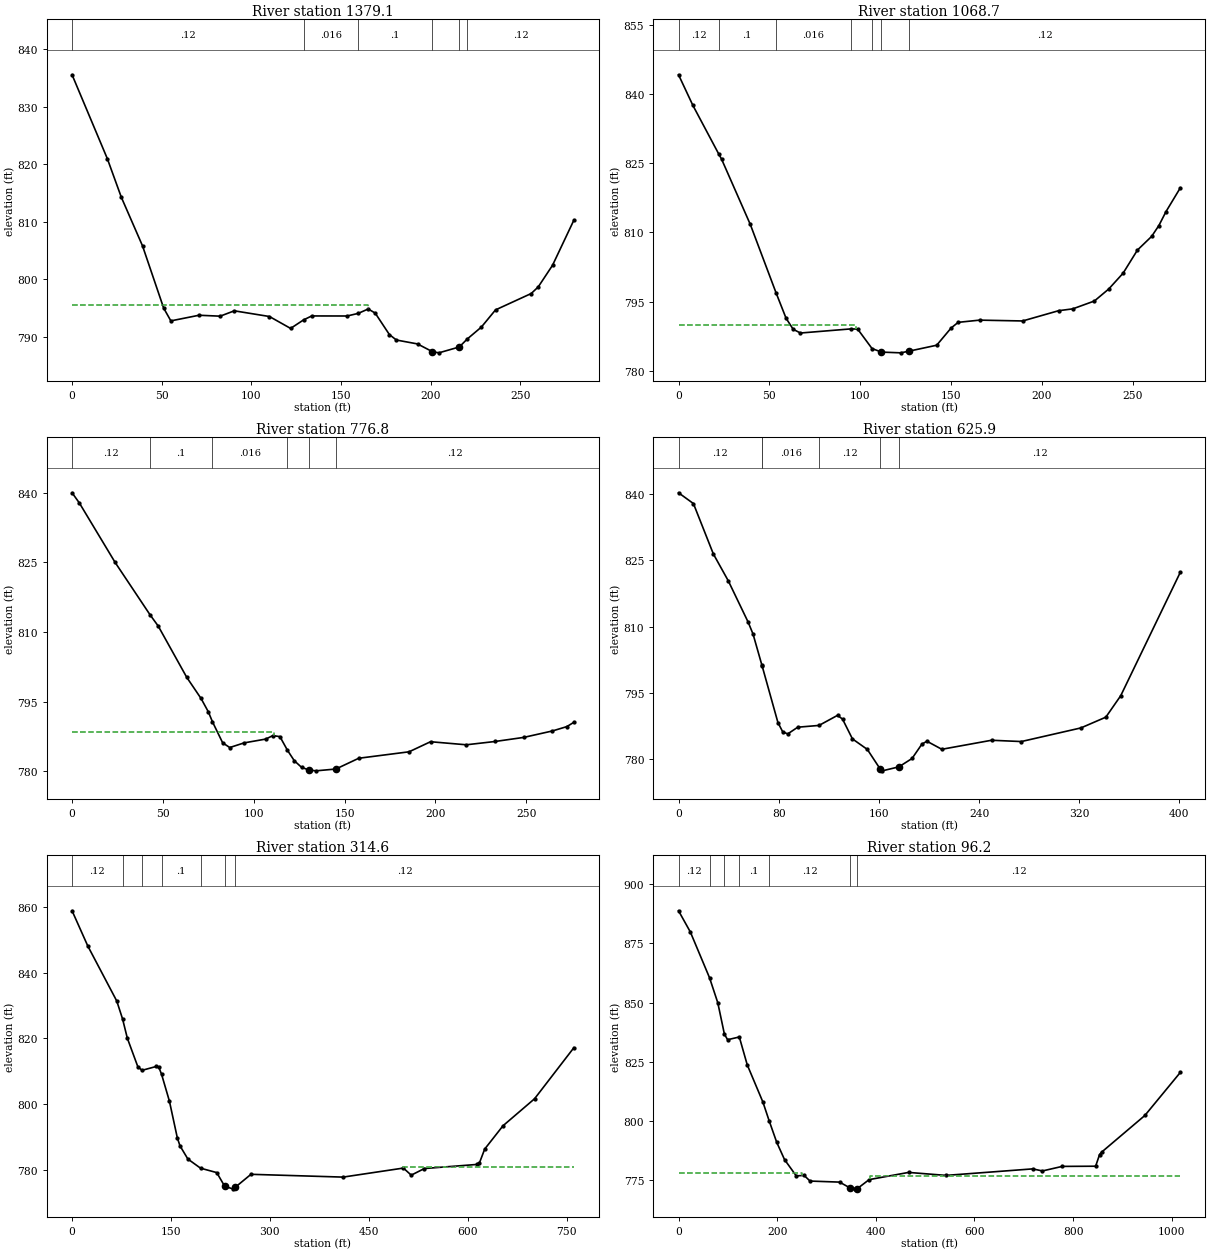
Type RM Length L Ch R = 1 ,1379.1  ,322.6,310.4,298.1
XS GIS Cut Line= 3
     1754823.591      360085.426     1755026.083      360035.819
     1755095.531      360019.336
#Sta/Elev= 30
       0  835.54    19.7  820.92    27.5  814.21    39.3  805.77    51.1  794.94
    55.1  792.72    70.8   793.7    82.6  793.54    90.5  794.47   110.1  793.48
   121.9  791.41  129.18 792.901   133.7  793.58   153.4  793.57  159.59 794.022
   165.2  794.79   169.1  794.07     177  790.34   180.9  789.39   192.7  788.71
     201  787.36   204.6  787.16     216  788.18  220.38789.5534   228.3  791.64
   236.2  794.63   256.1  797.48     260  798.62     268  802.39   279.9  810.24
#Mann= 6 ,-1 , 0
       0     .12       0  129.18    .016       0  159.59      .1       0
     201    .045       0     216      .1       0  220.38     .12       0
#XS Ineff= 2 , 0
          165.33  795.51
Permanent Ineff=
       F       F
Bank Sta=201,216
XS Rating Curve= 0 ,0
Exp/Cntr=0.3,0.1

Type RM Length L Ch R = 1 ,1068.7  ,291.9,291.9,291.9
XS GIS Cut Line= 2
     1755058.384      360399.483     1755255.867      360206.341
#Sta/Elev= 30
       0  844.13     7.9   837.5   22.01827.0684    23.7  825.86    39.5  811.74
   53.66796.9516    59.2  791.42    63.1  789.04    67.1  788.23   94.97789.1265
    98.6  789.08   106.5784.8718   111.7   784.1   122.3  783.94   126.7  784.29
   142.1  785.59     150   789.3   153.9  790.54   165.7  791.02   189.4  790.84
   209.2  793.06     217  793.46   228.9  795.16   236.8  797.76   244.7  801.18
   252.6  806.19   260.4  809.14   264.4   811.5   268.3   814.5   276.2  819.66
#Mann= 7 ,-1 , 0
       0     .12       0   22.01      .1       0   53.66    .016       0
   94.97      .1       0   106.5     .12       0   111.7    .045       0
   126.7     .12       0
#XS Ineff= 2 , 0
           97.52  789.93
Permanent Ineff=
       F       F
Bank Sta=111.7,126.7
XS Rating Curve= 0 ,0
Exp/Cntr=0.3,0.1

Type RM Length L Ch R = 1 ,776.8   ,149.3,150.8,152.3
XS GIS Cut Line= 2
     1755248.272      360620.837     1755445.754      360427.695
#Sta/Elev= 30
       0  839.97       4  837.78    23.7  824.97   42.91813.6976    47.4  811.28
    63.1  800.24      71  795.67      75   792.8   77.26790.6675    82.9  786.12
    86.8  785.11    94.7  786.11   106.6  786.93   110.5  787.68   114.4  787.46
  118.57784.5084   122.3  782.28   126.3  780.85   130.2  780.29   134.2  780.09
   145.2  780.48   157.8   782.8   185.5  784.19   197.3  786.36     217   785.7
   232.8  786.41   248.6  787.29   264.4  788.68   272.3  789.61   276.2  790.54
#Mann= 6 ,-1 , 0
       0     .12       0   42.91      .1       0   77.26    .016       0
  118.57     .12       0   130.2    .045       0   145.2     .12       0
#XS Ineff= 2 , 0
          111.15  788.41
Permanent Ineff=
       F       F
Bank Sta=130.2,145.2
XS Rating Curve= 0 ,0
Exp/Cntr=0.3,0.1

Type RM Length L Ch R = 1 ,625.9   ,295.4,311.4,326.6
XS GIS Cut Line= 2
     1755312.003      360752.353     1755616.691      360491.936
#Sta/Elev= 30
       0  840.24    11.9   837.8    27.8  826.42    39.7  820.36    55.6  811.01
    59.5  808.32   66.54801.3304   66.76801.1125    79.4   788.3    83.3  786.17
    87.3  785.76    95.2  787.26  112.22787.6632     127  789.94     131  789.09
   138.9  784.62   150.8  782.24     161  777.84   162.7   777.4     176   778.3
   186.5  780.19   194.4  783.44   198.4  784.09   210.3  782.27     250  784.31
   273.8  784.02   321.4   787.1   341.3  789.53   353.2  794.38   400.8  822.28
#Mann= 6 ,-1 , 0
       0     .12       0   66.54      .1       0   66.76    .016       0
  112.22     .12       0     161    .045       0     176     .12       0
Bank Sta=161,176
XS Rating Curve= 0 ,0
Exp/Cntr=0.3,0.1

Type RM Length L Ch R = 1 ,314.6   ,231.5,218.3,205.7
XS GIS Cut Line= 3
     1755285.962      360921.623     1755680.927      360916.415
     1755793.774      360568.325
#Sta/Elev= 30
       0  858.79    23.9  848.05    67.8  831.32   76.63825.8341    83.8  820.02
    99.8   811.3  106.17810.2423   127.7  811.42   131.7  811.11  135.71809.0425
   147.6  800.87   159.6   789.7   163.6  787.28   175.6  783.25  194.79780.4694
   219.4  779.12   231.4  774.97   243.4  774.18   247.4  774.65   271.3   778.6
   410.9  777.75   502.4   780.5   514.3  778.34   534.2  780.36   613.8   781.6
   617.7  782.06   625.7  786.28   653.5  793.38   701.3  801.59   760.9  817.12
#Mann= 7 ,-1 , 0
       0     .12       0   76.63      .1       0  106.17    .016       0
  135.71      .1       0  194.79     .12       0   231.4    .045       0
   247.4     .12       0
#XS Ineff= 2 , 0
                          501.96          780.95
Permanent Ineff=
       F       F
Bank Sta=231.4,247.4
XS Rating Curve= 0 ,0
Exp/Cntr=0.3,0.1

Type RM Length L Ch R = 1 ,96.2    ,84.6,96.2,108
XS GIS Cut Line= 4
     1755212.486      361111.393     1755485.055      361168.685
     1755639.569      361076.671     1755823.597      360548.893
#Sta/Elev= 30
       0  888.76    23.9  879.83   62.85860.4914    79.6  849.93   93.03836.6769
    99.5  834.35  123.21835.5042   139.3  823.74   171.1  808.01  183.57800.2224
     199  791.09   214.9  783.76   238.7  776.88   254.6  777.09   266.6   774.7
   326.5  774.26   347.7   771.8   358.4  771.42   362.7  771.55   386.4  775.31
   466.4  778.35   542.2  777.09   717.9  779.84   737.8  778.97   777.8  780.89
   845.6  780.97   853.6  785.89   857.6  786.88   945.4  802.38  1017.3  820.55
#Mann= 7 ,-1 , 0
       0     .12       0   62.85      .1       0   93.03    .016       0
  123.21      .1       0  183.57     .12       0   347.7    .045       0
   362.7     .12       0
#XS Ineff= 2 , 0
          250.15  777.97  388.49          776.68
Permanent Ineff=
       F       F
Bank Sta=347.7,362.7
XS Rating Curve= 0 ,0
Exp/Cntr=0.3,0.1
LCMann Table=0

Chan Stop Cuts=-1
Use User Specified Reach Order=0
Composite Channel Slope=5